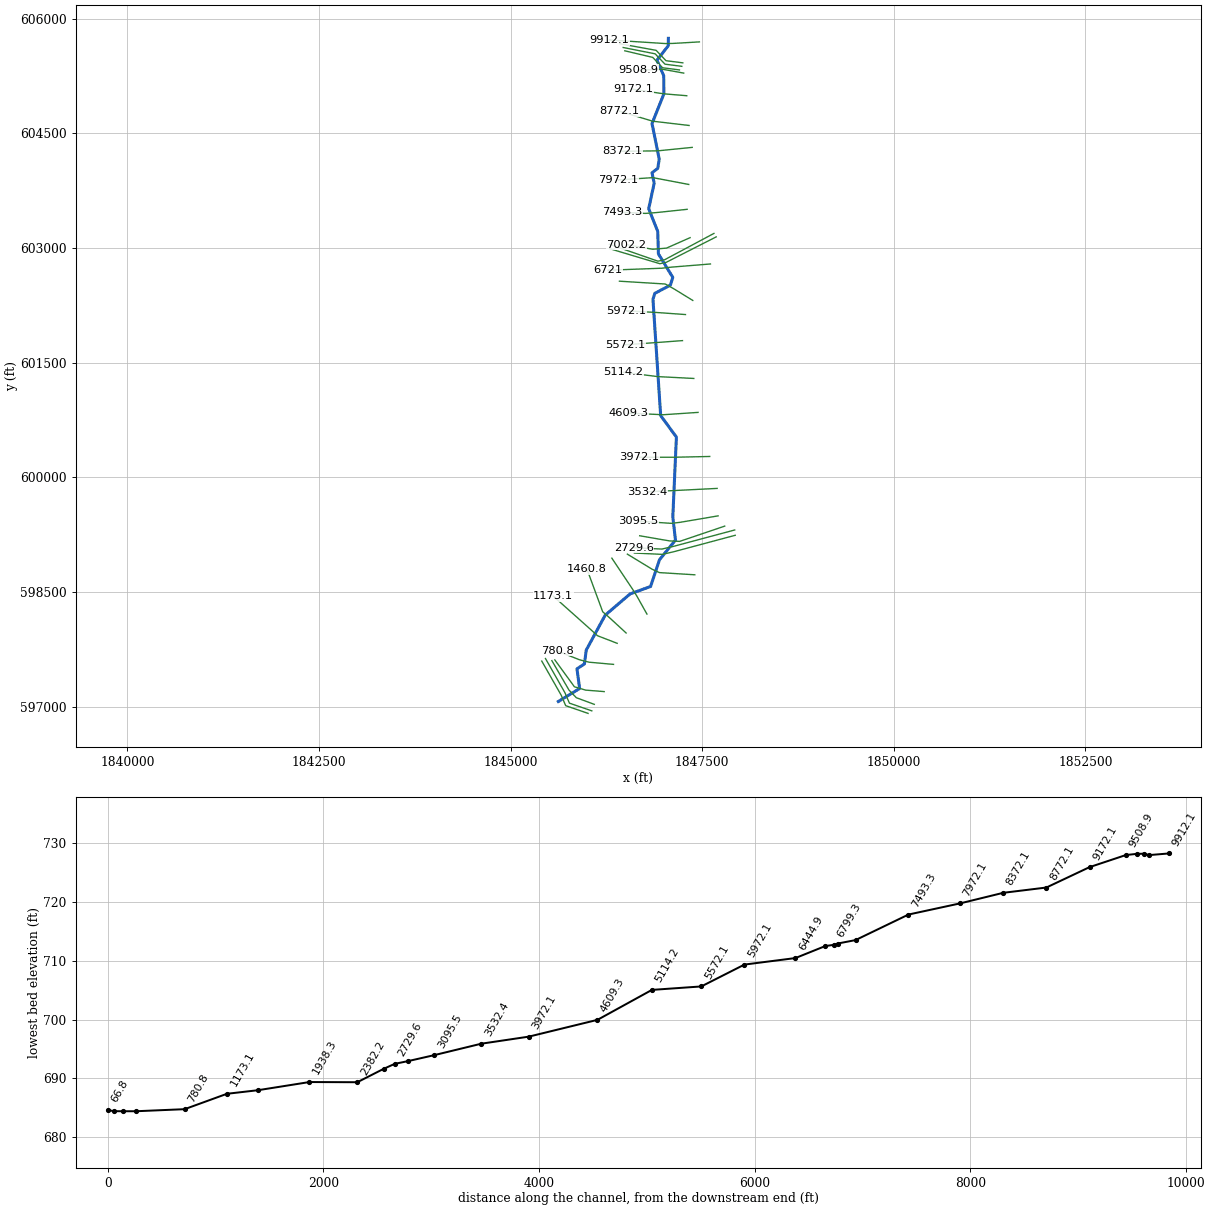
--- BigCreek.prj (project) ---

Proj Title=BigCreek
Current Plan=p01
Default Exp/Contr=0,0
English Units
Geom File=g01
Flow File=f01
Plan File=p01
BEGIN DESCRIPTION:
AMEC Environment & Infrastructure, 2013
Projection: NAD 1983 State Plane West Virginia South FIPS 4702 (US Feet)
Vertical Datum: NAVD 1988
END DESCRIPTION:
DSS Export Rating Curves= 0
DSS Export Rating Curve Sorted= 0
DSS Export Volume Flow Curves= 0
DXF OffsetX= 0
DXF OffsetY= 0
DXF ScaleX= 0
DXF ScaleY= 0

--- BigCreek.p01 (plan) ---

Plan Title=Floodplain
Program Version=4.00
Geom File=g01
Flow File=f01
K Sum by GR=0
Std Step Tol=0.01
Critical Tol=0.01
Num of Std Step Trials=20
Max Error Tol=0.3
Flow Tol Ratio=0.001
Split Flow NTrial=30
Split Flow Tol=0.02
Split Flow Ratio=0.02
Log Output Level=0
Friction Slope Method=1
Unsteady Friction Slope Method=2
Unsteady Bridges Friction Slope Method=1
Global Log Level=0
CheckData=False
Run HTab=0
Run UNet=0
Run PostProcess=0
UNET Theta=0
UNET Theta Warmup=0
UNET ZTol=0
UNET ZSATol=0
UNET MxIter=0
UNET MaxInSteps=0
UNET DtIC=0
UNET DtMin=0
UNET MaxCRTS=0
UNET WFStab=0
UNET SFStab=0
UNET WFX=0
UNET SFX=0
UNET DSS MLevel=0
UNET DZMax Abort=0
UNET Convert EG Bridges=0
UNET Use Existing IB Tables=0
UNET Froude Limit=0
UNET Froude Power=0
Write IC File=0
Echo Input=False
Echo Output=False
Write Detailed=0

--- BigCreek.f01 (steady flow) ---

Flow Title=NFF Regression Equation
Program Version=4.10
Number of Profiles= 1
Profile Names=P100yr
River Rch & RM=BigCreek,Main            ,9912.1
1071.559
River Rch & RM=BigCreek,Main            ,7002.2
 1128.29
River Rch & RM=BigCreek,Main            ,6444.9
1295.857
River Rch & RM=BigCreek,Main            ,4609.3
1340.407
River Rch & RM=BigCreek,Main            ,1460.8
1436.945
River Rch & RM=BigCreek,Main            ,1173.1
1518.907
River Rch & RM=BigCreek,Main            ,213.8
1525.833
Boundary for River Rch & Prof#=BigCreek,Main            , 1
Up Type= 0
Dn Type= 3
Dn Slope=0.00078
DSS Import GetInterval= 0
DSS Import GetPeak= 0
DSS Import FillOption= 0

--- BigCreek.g01 (geometry) ---

Geom Title=USGS 3m DEM
Program Version=4.10

River Reach=BigCreek        ,Main
Reach XY= 30
     1847058.491      605741.422     1847056.759      605644.166
     1846909.148      605454.858     1846997.947      605252.319
     1846999.478      605013.739      1846844.93      604626.446
     1846938.735      604161.013     1846919.636      604041.179
     1846844.961      603983.864     1846872.755      603846.666
     1846801.593      603512.717     1846919.676      603216.244
     1846928.374      602922.741     1847115.953      602615.353
     1847084.697      602514.622     1846881.447      602407.138
     1846857.197      602328.784     1846957.736      600808.606
     1847162.943      600527.835     1847116.101      599482.338
     1847151.019      599182.286     1846942.457      598923.111
     1846826.114      598574.028     1846558.666       598476.76
     1846233.667      598198.625     1845986.569      597742.178
      1845963.02      597561.491     1845865.767      597497.228
     1845900.514      597240.198     1845622.732      597070.029

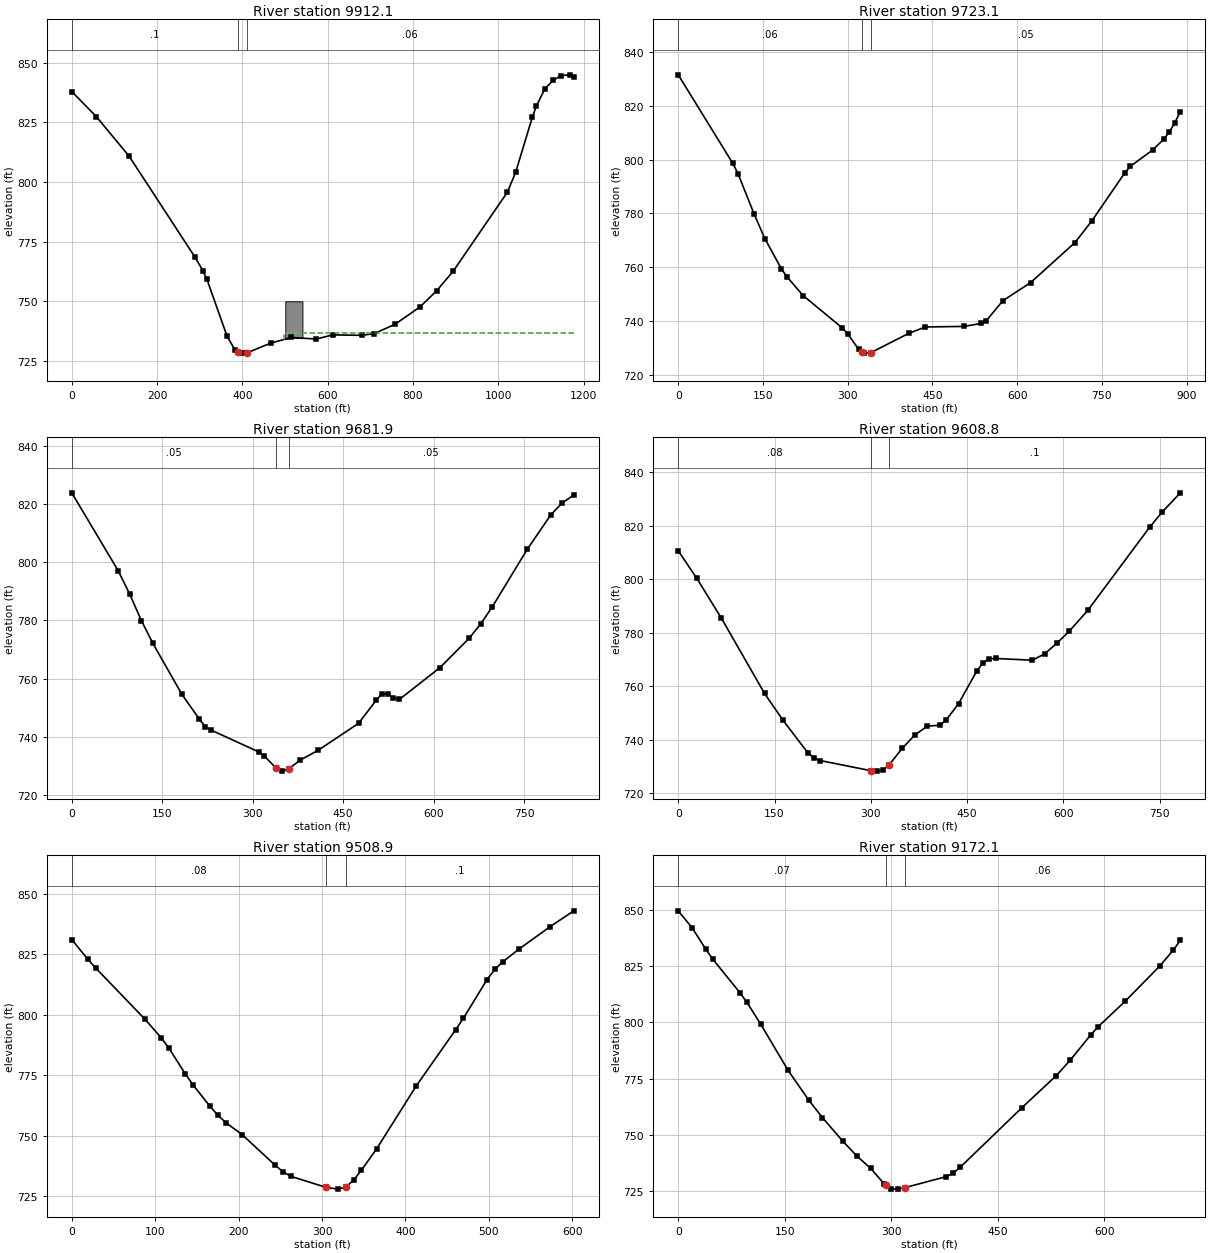
Type RM Length L Ch R = 1 ,9912.1  ,207.6,189,170.1
XS GIS Cut Line= 4
       1847463.1      605694.808     1847117.918      605674.843
     1847017.223      605673.107     1846288.057      605719.982
#Sta/Elev= 30
       0  837.87    57.6  827.38   134.5  810.79   288.1  768.73   307.3  762.88
     317  759.15   364.1  735.35   382.4  729.75   389.5  728.74   400.7   728.3
   409.8  728.35     466  732.47   514.7  734.85   573.1  734.21   612.1  735.94
   680.3  735.76   709.5  736.51   758.2  740.42   816.7  747.71   855.6  754.44
   894.6  762.71  1021.3  795.74  1040.8  804.13  1079.7  827.09  1089.5  831.93
  1108.9  838.94  1128.4  842.58  1147.9  844.59  1167.4  844.89  1177.1  844.12
#Mann= 3 , 0 , 0
       0      .1       0   389.5    .045       0   409.8     .06       0
#XS Ineff= 2 , 0
                          497.12          736.88
Permanent Ineff=
       F       F
#Block Obstruct= 1 ,-1
  500.61  540.73  750.01
Bank Sta=389.5,409.8
XS Rating Curve= 0 ,0
Exp/Cntr=0.3,0.1

Type RM Length L Ch R = 1 ,9723.1  ,41.2,41.2,41.2
XS GIS Cut Line= 4
      1847246.52      605420.937     1847027.336      605449.148
      1846898.43      605584.565      1846425.34      605670.937
#Sta/Elev= 30
       0  831.53    96.1  798.78   105.7  794.82   134.5  779.68   153.7  770.45
   182.6  759.39   192.2  756.48     221  749.44   289.9  737.47   299.7  735.31
   319.4  729.42     326  728.47   329.2  728.01     341  728.19     408  735.35
   437.4  737.74   506.1  737.95   535.5  739.04   545.4  740.08   574.8  747.52
   623.9  754.24   702.4  769.15   731.8  777.06   790.7  795.08   800.5  797.52
   839.8  803.55   859.4  807.52   869.2  810.17     879  813.63   888.9  817.88
#Mann= 3 , 0 , 0
       0     .06       0     326    .045       0     341     .05       0
Bank Sta=326,341
XS Rating Curve= 0 ,0
Exp/Cntr=0.3,0.1

Type RM Length L Ch R = 1 ,9681.9  ,85.2,73.1,61.9
XS GIS Cut Line= 4
     1847233.499      605375.364     1847014.315      605403.575
     1846885.409      605538.992     1846469.177      605621.457
#Sta/Elev= 30
       0  823.82    76.9   797.1    96.1  789.03   115.3  779.97   134.5  772.11
   182.6   754.6   211.4  746.14     221  743.56   230.8  742.36   309.6  734.88
   319.4  733.41   339.1  729.18   348.9  728.25   359.7  729.05   378.4     732
     408  735.35   475.5  744.67   504.4  752.54     514  754.69   523.7  754.85
   533.3  753.45     543  752.86   610.5  763.82   658.7  773.87     678  778.85
   697.3  784.73   755.1  804.44   793.7  816.13     813  820.39   832.3  823.04
#Mann= 3 , 0 , 0
       0     .05       0   339.1    .045       0   359.7     .05       0
Bank Sta=339.1,359.7
XS Rating Curve= 0 ,0
Exp/Cntr=0.3,0.1

Type RM Length L Ch R = 1 ,9608.8  ,68.8,100,129.3
XS GIS Cut Line= 4
     1847202.249      605328.489     1846983.065        605356.7
     1846854.159      605492.117      1846490.01      605578.489
#Sta/Elev= 30
       0  810.64    28.8  800.36    67.3   785.4   134.5  757.26   163.3  747.22
   201.8   735.1   211.4  733.24     221  732.18   299.7  728.41   309.6  728.22
   319.4   728.6   328.2  730.45   348.9  736.72   368.6  741.74   388.3  745.07
     408  745.37   417.6  747.42   436.7  753.44   465.5  765.83   475.1  768.78
   484.7  770.16   494.3  770.36   551.9   769.7   571.1  772.14   590.3  776.17
   609.5  780.63   638.3  788.42   734.2  819.39   753.4  824.98   782.2  832.31
#Mann= 3 , 0 , 0
       0     .08       0   299.7    .045       0   328.2      .1       0
Bank Sta=299.7,328.2
XS Rating Curve= 0 ,0
Exp/Cntr=0.3,0.1

Type RM Length L Ch R = 1 ,9508.9  ,339,336.8,333.7
XS GIS Cut Line= 4
     1847258.239      605286.822     1846980.895      605337.603
     1846888.013      605333.263     1846661.234      605327.187
#Sta/Elev= 30
       0  831.04    19.4  822.86    29.2  819.12    87.5  798.24     107  790.59
   116.7   786.1   136.1  775.56   145.8  770.86   165.3  762.36     175  758.56
   184.7  755.47   204.2  750.52   243.1   738.1   252.8  735.29   262.5  733.32
  304.54  728.77   319.2  728.02   328.4  728.89   337.7  731.69     347  735.76
   365.6  744.75   412.8  770.58     460  793.75   469.5   798.6   497.8  814.56
   507.3   818.8   516.7  821.88   535.6     827   573.4  836.39   601.8  842.91
#Mann= 3 , 0 , 0
       0     .08       0  304.54    .045       0   328.4      .1       0
Bank Sta=304.54,328.4
XS Rating Curve= 0 ,0
Exp/Cntr=0.3,0.1

Type RM Length L Ch R = 1 ,9172.1  ,400.1,400,396.2
XS GIS Cut Line= 3
     1847298.387      604991.032     1846999.478      605015.811
     1846596.564      605075.667
#Sta/Elev= 30
       0   849.6    19.4  842.13    38.7  832.61    48.4  828.24    87.1  813.14
    96.8   808.9   116.1   799.3   154.8  778.69   183.8  765.53   203.2   757.7
   232.2  747.13   251.6  740.69   270.9  735.22   290.3  728.26   292.4   727.8
   299.9  726.14   309.6  725.96   319.3  726.64   377.5   731.5   387.2  733.02
   396.9  735.58   484.2  762.15   532.7  776.43   552.1  783.21   581.2  794.52
   590.9   797.9   629.7  809.45   678.2  825.01   697.6  832.23   707.3  836.49
#Mann= 3 , 0 , 0
       0     .07       0   292.4    .045       0   319.3     .06       0
Bank Sta=292.4,319.3
XS Rating Curve= 0 ,0
Exp/Cntr=0.3,0.1

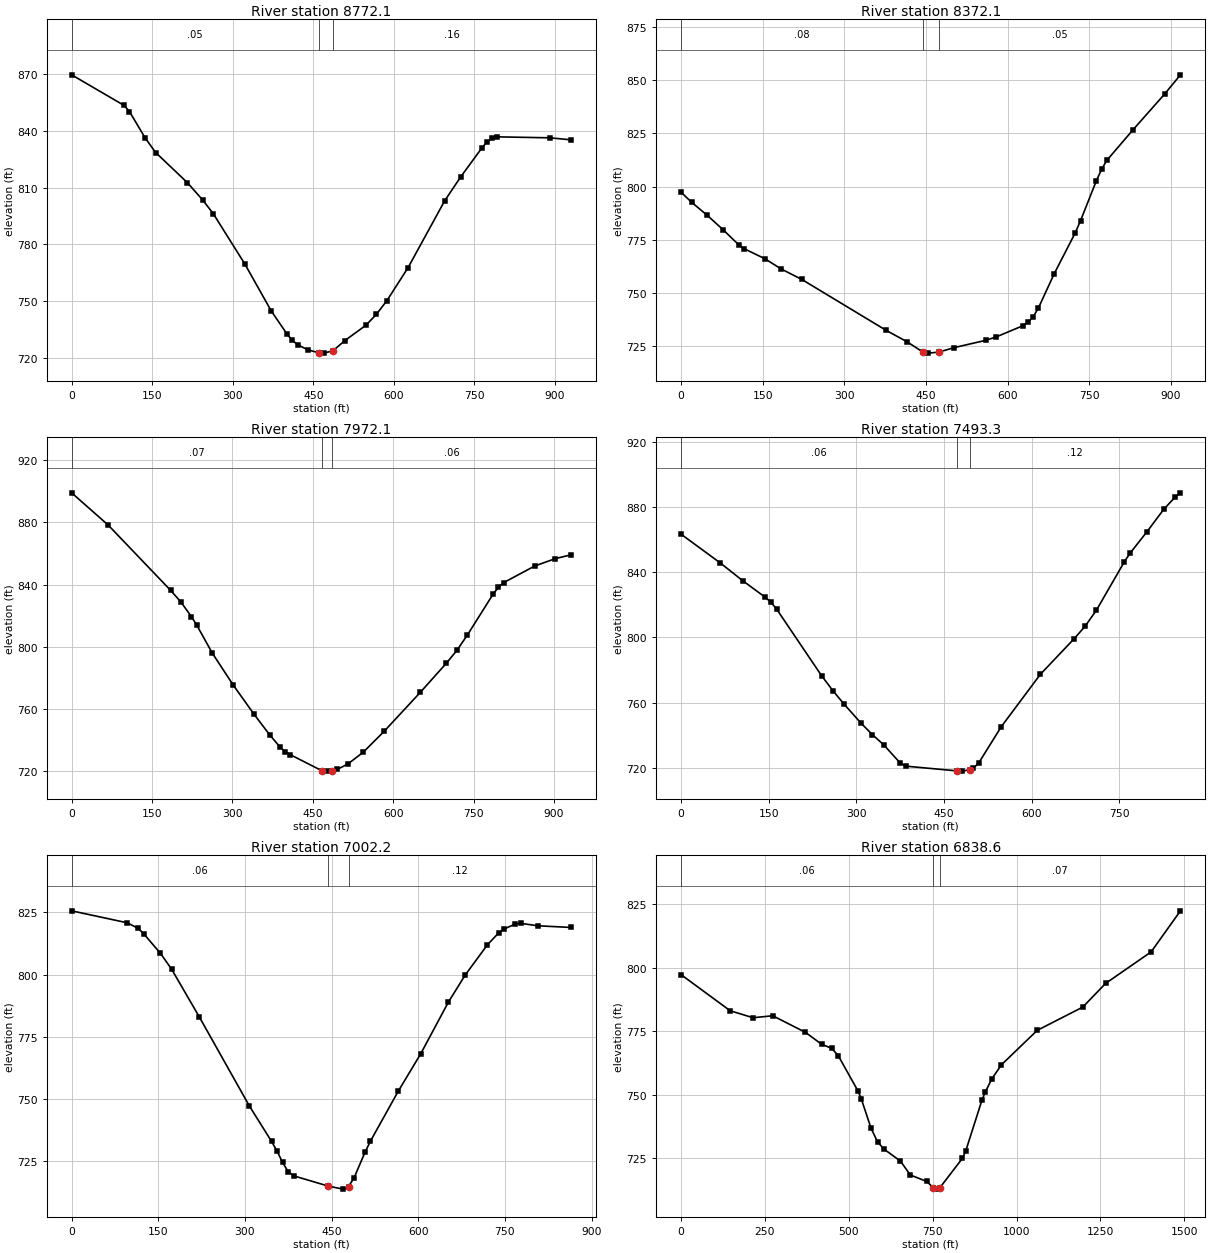
Type RM Length L Ch R = 1 ,8772.1  ,394.8,400,406.7
XS GIS Cut Line= 3
     1847328.901      604602.023     1846852.844      604658.108
     1846421.698      604788.894
#Sta/Elev= 30
       0  869.78    97.8  853.56   107.6  850.37     137  836.32   156.5  828.65
   215.2  812.79   244.6  803.35   264.1  796.12   322.8  769.51   371.7  744.79
   401.1  732.54   410.9  729.26   420.6  726.97   440.2  724.18   459.8  722.73
   469.6  722.49   486.8  723.78   508.7  729.12   547.9  737.25   567.5  743.05
   587.1  750.32   626.3  767.69   694.8  803.23   724.2  815.69   763.4  830.92
   773.2  834.16     783  836.19   792.8  836.95   890.7  836.44   929.9  835.37
#Mann= 3 , 0 , 0
       0     .05       0   459.8    .045       0   486.8     .16       0
Bank Sta=459.8,486.8
XS Rating Curve= 0 ,0
Exp/Cntr=0.3,0.1

Type RM Length L Ch R = 1 ,8372.1  ,406.6,400,401
XS GIS Cut Line= 3
       1847369.5      604315.624     1846917.889      604270.081
     1846454.143      604264.787
#Sta/Elev= 30
       0  797.33    19.3  792.63    48.3  786.41    77.3  779.67   106.2  772.52
   115.9  770.75   154.5  765.96   183.5  761.27   222.1  756.25   376.6  732.36
   415.3  726.93   444.2  722.15   453.9  721.59   473.2  722.04   502.2   724.2
   560.2  727.63   579.5  729.25   627.8  734.44   637.5  736.09   647.1   738.7
   656.8  742.86   685.8  758.99   724.4  778.19   734.1  783.91   763.1  802.63
   772.8  808.08   782.4  812.29   830.7  826.73   888.7  843.53   917.7  852.55
#Mann= 3 , 0 , 0
       0     .08       0   444.2    .045       0   473.2     .05       0
Bank Sta=444.2,473.2
XS Rating Curve= 0 ,0
Exp/Cntr=0.3,0.1

Type RM Length L Ch R = 1 ,7972.1  ,471.9,478.8,478.3
XS GIS Cut Line= 3
     1847324.415      603830.807     1846856.435      603919.966
     1846401.979      603889.655
#Sta/Elev= 30
       0  899.06    68.1  878.32   184.7  836.23   204.2  828.58   223.6  819.23
   233.3  813.93   262.5  795.78   301.4  775.28   340.3  756.45   369.4  743.23
   388.9  735.26   398.6  732.31   408.3  730.32   466.7  720.09   476.4  719.79
   486.1   720.1   495.8  720.95   515.2  724.33   544.2     732     583  745.39
   650.8  770.62   699.3  789.34   718.7  797.53     738  807.24   786.5  833.85
   796.2  838.16   805.9  841.19     864  851.91   902.8  856.72   931.9  859.12
#Mann= 3 , 0 , 0
       0     .07       0   466.7    .045       0   486.1     .06       0
Bank Sta=466.7,486.1
XS Rating Curve= 0 ,0
Exp/Cntr=0.3,0.1

Type RM Length L Ch R = 1 ,7493.3  ,490.8,491.1,491.8
XS GIS Cut Line= 4
     1847303.531      603505.703     1846901.512      603463.037
     1846758.282      603452.187     1846452.293      603467.378
#Sta/Elev= 30
       0  863.36    67.4  845.62   105.9  834.69   144.4  824.53     154  821.48
   163.6  817.33   240.6  776.39   259.9  767.24   279.1  758.93     308  747.32
   327.3   740.3   346.5  734.12   375.4  722.69     385  720.93   471.3  718.06
   480.9  717.89   494.2  718.71     500  719.56   509.6  723.11   547.9   745.2
   614.9   777.4   672.4  799.13   691.5  806.94   710.7  816.76   758.5  846.47
   768.1  851.65   796.8  864.72   825.6  878.52   844.7  885.91   854.3  888.72
#Mann= 3 , 0 , 0
       0     .06       0   471.3    .045       0   494.2     .12       0
Bank Sta=471.3,494.2
XS Rating Curve= 0 ,0
Exp/Cntr=0.3,0.1

Type RM Length L Ch R = 1 ,7002.2  ,161.1,163.6,165.9
XS GIS Cut Line= 4
     1847341.616      603134.912      1847033.89      602998.628
     1846853.769      602983.437     1846511.755      603042.898
#Sta/Elev= 30
       0  825.65    96.2  820.83   115.4  818.56     125  816.35   153.8   808.5
   173.1  802.12   221.2  782.82   307.7  747.01   346.1  732.73   355.6  728.85
   365.1  724.28   374.6  720.64   384.1  718.91   444.2  714.76   469.8  713.54
   479.3  714.59   488.8  718.06   507.8   728.4   517.3  732.91   565.5  753.05
   604.1  768.01   652.3  788.95   681.2  799.76   719.8  812.01   739.1  816.73
   748.7  818.37     768  820.32   777.7   820.6   806.6  819.63   864.5  818.95
#Mann= 3 , 0 , 0
       0     .06       0   444.2    .045       0   479.3     .12       0
Bank Sta=444.2,479.3
XS Rating Curve= 0 ,0
Exp/Cntr=0.3,0.1

Type RM Length L Ch R = 1 ,6838.6  ,39,39.3,39.6
XS GIS Cut Line= 4
      1847652.64      603190.468      1847006.98      602844.982
     1846921.911      602827.621     1846289.793      603048.107
#Sta/Elev= 30
       0  797.26   146.5  783.06   214.8  780.31   273.4  781.09     371  774.56
   419.8  769.82   449.1  768.31   468.7  765.39   527.2   751.6     537  748.57
   566.3  736.93   585.8  731.53   605.4  728.64   654.2  723.96   683.5  718.51
   732.3  715.98   751.6  713.57   761.2  712.96   771.9  713.56   838.5  725.02
   848.2  727.77   896.7   747.8   906.4  750.97   925.8  756.14   954.9   761.8
  1061.7  775.35  1197.5  784.49  1265.4  793.78  1401.2  806.18  1488.6  822.32
#Mann= 3 , 0 , 0
       0     .06       0   751.6    .045       0   771.9     .07       0
Bank Sta=751.6,771.9
XS Rating Curve= 0 ,0
Exp/Cntr=0.3,0.1

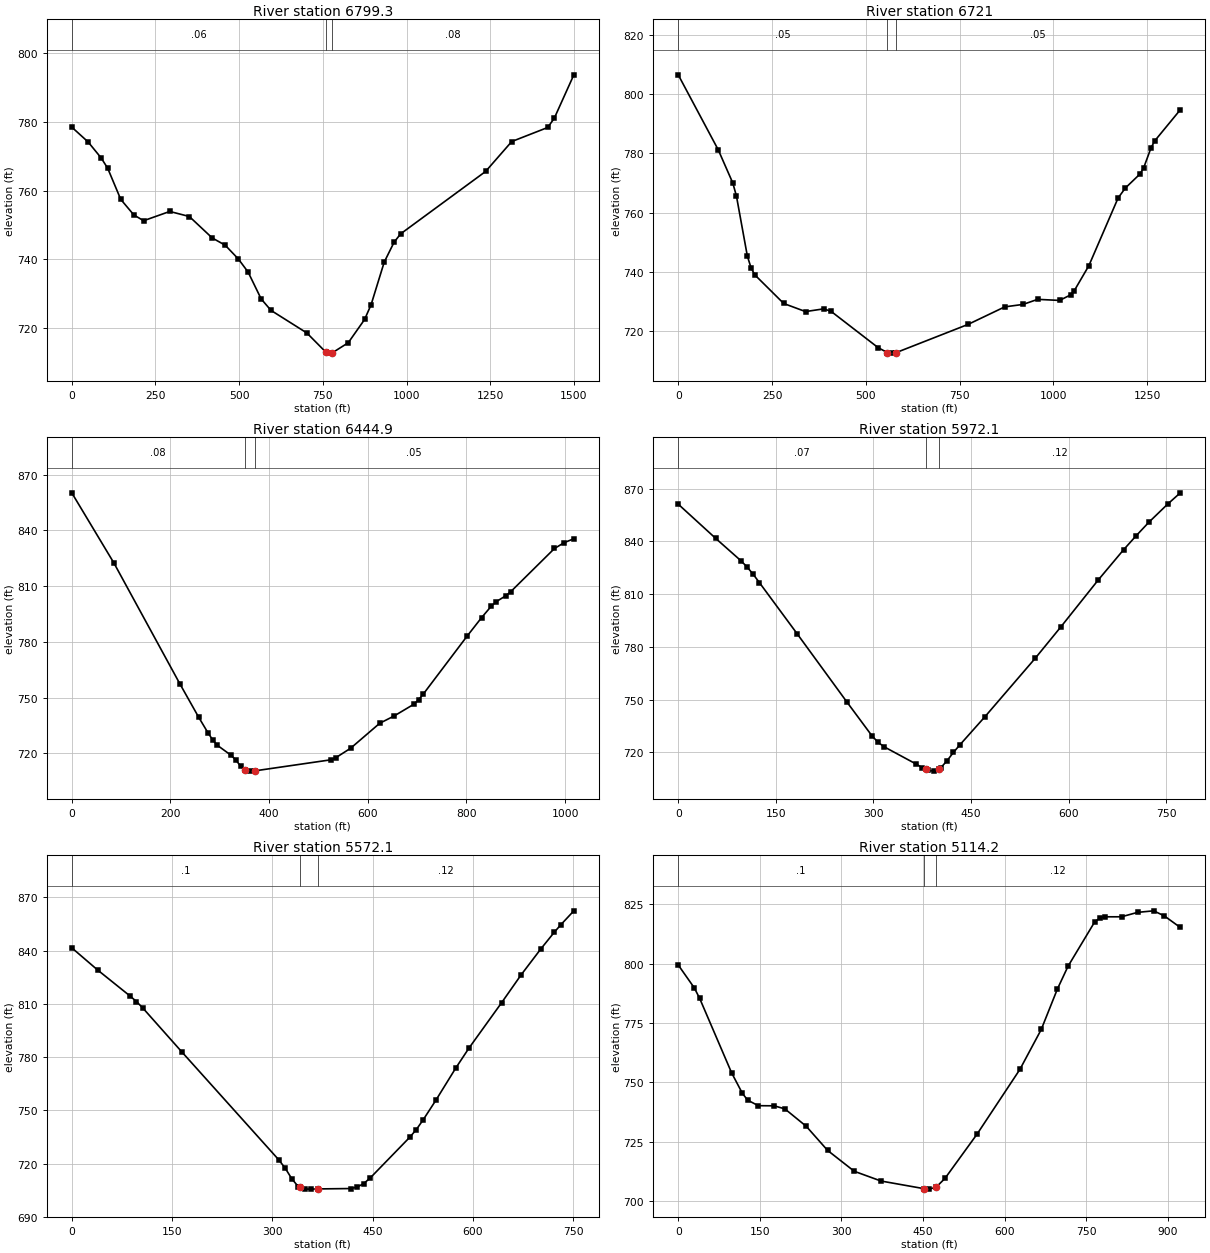
Type RM Length L Ch R = 1 ,6799.3  ,81.5,78.3,74.7
XS GIS Cut Line= 4
     1847682.154      603145.329     1847030.374      602812.864
     1846947.909      602794.417     1846293.005      602990.815
#Sta/Elev= 30
       0  778.53    48.8  774.22    87.8  769.56   107.3  766.56   146.3   757.5
   185.4  752.97   214.6  751.28   292.7  753.98   351.2  752.51   419.5  746.27
   458.5  744.14   497.5  740.16   526.8  736.33   565.8  728.51   595.1  725.18
   702.4  718.59     759  713.02   769.2  712.73   778.6  712.84     826  715.76
   874.8  722.53   894.3  726.86   933.4  739.22   962.7  744.99   982.2  747.44
  1236.2  765.62  1314.3  774.33  1421.8  778.43  1441.3  781.09  1499.9  793.76
#Mann= 3 , 0 , 0
       0     .06       0     759    .045       0   778.6     .08       0
Bank Sta=759,778.6
XS Rating Curve= 0 ,0
Exp/Cntr=0.3,0.1

Type RM Length L Ch R = 1 ,6721    ,289,276.1,263.2
XS GIS Cut Line= 4
     1847607.241      602791.162     1847095.262      602749.496
      1846973.56      602735.607     1846272.171      602709.565
#Sta/Elev= 30
       0  806.56   106.6  781.22   145.4  770.01   155.1  765.61   184.2   745.3
   193.8  741.44   203.5  739.04   281.1  729.29   339.2  726.56   387.7  727.48
   407.1  726.66   532.5  714.39   557.1  712.71   570.2  712.52   579.6  712.64
   772.6  722.24   870.1  728.15   918.9  728.98   957.8  730.69  1016.3  730.33
  1045.6   732.2  1055.3  733.59  1094.3  742.07  1172.3  764.97  1191.8  768.34
  1230.8  773.08  1240.6  775.22    1260  781.91  1269.8  784.24    1338  794.76
#Mann= 3 , 0 , 0
       0     .05       0   557.1    .045       0   579.6     .05       0
Bank Sta=557.1,579.6
XS Rating Curve= 0 ,0
Exp/Cntr=0.3,0.1

Type RM Length L Ch R = 1 ,6444.9  ,462.6,472.8,482.7
XS GIS Cut Line= 4
     1847376.772      602314.166     1847133.716      602463.905
     1847018.699      602529.009     1846419.741      602565.902
#Sta/Elev= 30
       0  860.25    85.6   822.4   218.9  757.56   256.9  739.64     276  731.14
   285.5  727.35   294.9  724.42   323.2  718.95   332.7  716.39   342.1  713.21
   350.7  711.13     361  710.48   370.4   710.6   525.9   716.6   535.7  717.79
   565.2  722.79   624.2  736.23   653.8  740.22   693.1  746.43   702.9  748.84
   712.8  752.04   801.3  783.12   830.8  793.13   850.5  799.29   860.3  801.65
     880   804.9   889.8  807.05   978.4  830.29   998.1  833.44  1017.7  835.54
#Mann= 3 , 0 , 0
       0     .08       0   350.7    .045       0   370.4     .05       0
Bank Sta=350.7,370.4
XS Rating Curve= 0 ,0
Exp/Cntr=0.3,0.1

Type RM Length L Ch R = 1 ,5972.1  ,395.1,400,401.2
XS GIS Cut Line= 3
     1847281.286      602129.704     1846888.369      602157.885
     1846510.887      602177.447
#Sta/Elev= 30
       0  861.12    57.6  841.67    96.1  829.06   105.7  825.49   115.3  821.22
   124.9  816.48   182.6  787.56   259.4  748.62   297.8  729.46   307.4  725.67
   317.1  723.09   365.1  713.52   374.7  711.42  380.38  710.43   384.3  709.73
   393.9  709.37   401.4  710.83   403.6  711.26   413.3   715.3     423  719.96
   432.7  724.18   471.5  740.28     549  773.59   587.8  791.16   645.9  818.12
   684.7  835.22   704.1   843.2   723.5  850.83   752.5  861.17   771.9  867.57
#Mann= 3 , 0 , 0
       0     .07       0  380.38    .045       0   401.4     .12       0
Bank Sta=380.38,401.4
XS Rating Curve= 0 ,0
Exp/Cntr=0.3,0.1

Type RM Length L Ch R = 1 ,5572.1  ,460.7,457.9,453.7
XS GIS Cut Line= 3
     1847242.223      601788.992     1846894.989      601762.968
     1846493.526      601734.739
#Sta/Elev= 30
       0  841.61    38.7   829.1      87   814.5    96.7  811.35   106.4  807.62
   164.4  783.03   309.5  722.16   319.2  717.42   328.9  711.54   338.5  707.12
   340.7   706.8   348.2   705.7     358  705.65   367.8  705.76   416.9  705.98
   426.7   706.8   436.6  708.81   446.4  712.01   505.3  734.85   515.1   739.2
   524.9   744.4   544.5  755.79     574  773.78   593.6  784.96   642.7  810.69
   672.1   826.5   701.6  841.11   721.2  850.27     731  854.52   750.7  862.45
#Mann= 3 , 0 , 0
       0      .1       0   340.7    .045       0   367.8     .12       0
Bank Sta=340.7,367.8
XS Rating Curve= 0 ,0
Exp/Cntr=0.3,0.1

Type RM Length L Ch R = 1 ,5114.2  ,504.7,504.9,506.5
XS GIS Cut Line= 3
     1847389.904      601294.105     1846919.816      601318.457
     1846471.079      601374.527
#Sta/Elev= 30
       0  799.42    29.4  789.83    39.2  785.46    98.1  754.03   117.7  745.47
   127.5  742.54   147.1  740.19   176.5  740.13   196.1  738.83   235.4  731.49
   274.6  721.35   323.6  712.57   372.6  708.48   451.1  705.28   460.9  705.06
   473.9  705.84   490.4   709.6   549.4  728.25     628  755.45   667.3  772.28
   696.8  789.22   716.5  798.88   765.6  817.59   775.5  819.24   785.3   819.7
   814.8  819.71   844.3  821.57   873.8  822.22   893.4   820.1   922.9  815.21
#Mann= 3 , 0 , 0
       0      .1       0   451.1    .045       0   473.9     .12       0
Bank Sta=451.1,473.9
XS Rating Curve= 0 ,0
Exp/Cntr=0.3,0.1

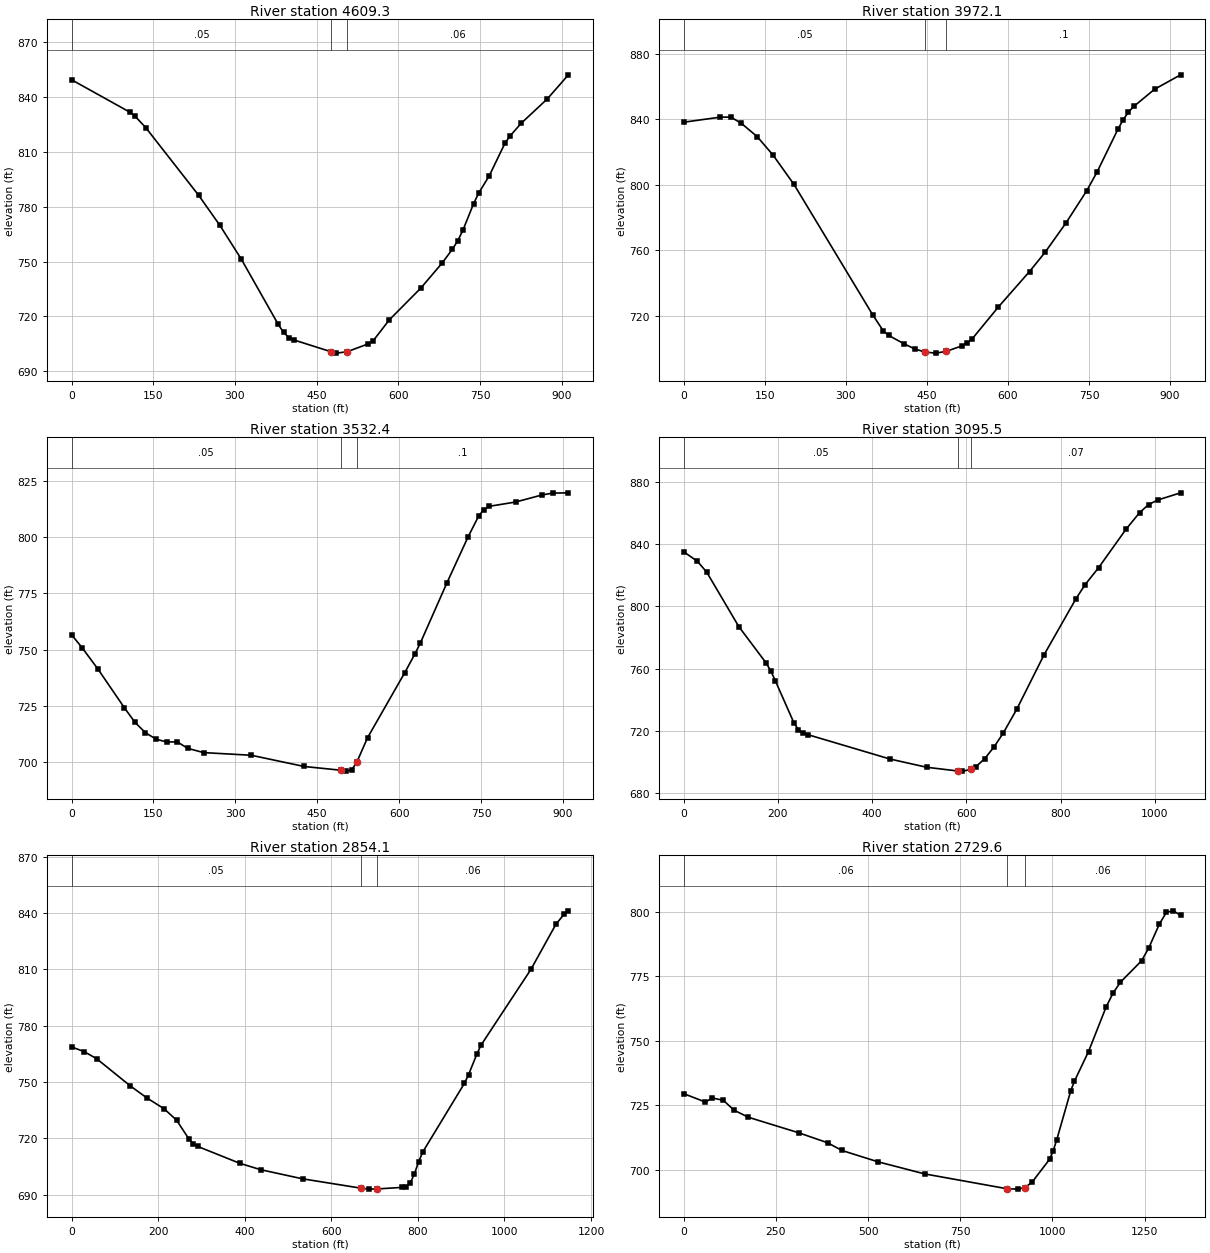
Type RM Length L Ch R = 1 ,4609.3  ,635.5,637.2,637.9
XS GIS Cut Line= 3
     1847445.214      600850.327     1846988.919       600819.71
      1846534.81      600840.895
#Sta/Elev= 30
       0  849.38     107  831.67   116.8  829.37   136.2  823.22   233.5  786.16
   272.4  769.74   311.4  751.43   379.5  715.62   389.2  711.26   398.9  708.48
   408.7  707.11   476.7  700.69   486.3  699.96   505.7   700.7   544.4  705.01
     554  706.85   583.1  718.09   641.1  735.52   679.8  749.05   699.1  756.76
   708.8  761.34   718.5  767.24   737.8  781.57   747.5  787.53   766.8  796.96
   795.8  814.87   805.5  818.86   824.9  825.47   873.2  838.89   911.9  852.06
#Mann= 3 , 0 , 0
       0     .05       0   476.7    .045       0   505.7     .06       0
Bank Sta=476.7,505.7
XS Rating Curve= 0 ,0
Exp/Cntr=0.3,0.1

Type RM Length L Ch R = 1 ,3972.1  ,439.1,439.7,440.7
XS GIS Cut Line= 3
     1847598.037      600274.059     1847131.694      600263.878
     1846678.716      600263.858
#Sta/Elev= 30
       0  838.15      68  841.27    87.5  841.24   106.9   837.4     136  829.35
   165.2  818.12   204.1  800.14   349.8  720.46   369.3  710.71     379  707.97
   408.2   702.7   427.6  699.66     447  697.72   466.4   697.1   485.7  698.16
   514.6  701.51   524.3  703.07   533.9  705.86   582.1  725.23   639.9  746.94
   668.8  758.73   707.4  776.64     746  796.41   765.2  807.93   803.8   834.1
   813.4  839.75     823   844.4   832.7  847.76   871.2  858.27   919.4   867.1
#Mann= 3 , 0 , 0
       0     .05       0     447    .045       0   485.7      .1       0
Bank Sta=447,485.7
XS Rating Curve= 0 ,0
Exp/Cntr=0.3,0.1

Type RM Length L Ch R = 1 ,3532.4  ,435.3,436.9,438.3
XS GIS Cut Line= 3
     1847694.612      599856.552     1847240.194      599833.492
     1846785.679      599812.081
#Sta/Elev= 30
       0  756.63    19.4   750.8    48.4  741.31    96.8  724.09   116.2  717.62
   135.5  712.97   154.9  710.11   174.3  708.86   193.6  708.92     213  706.02
     242  704.14   329.2  702.96     426  697.97   493.7  696.29   503.4   695.9
   513.1  696.42   522.8  700.03   542.1  710.73   609.9  739.53   629.3  748.19
     639  752.97   687.4  779.57   726.1  800.02   745.4  809.24   755.1  812.28
   764.8   813.7   813.2  815.61   861.6  818.75     881  819.58     910  819.71
#Mann= 3 , 0 , 0
       0     .05       0   493.7    .045       0   522.8      .1       0
Bank Sta=493.7,522.8
XS Rating Curve= 0 ,0
Exp/Cntr=0.3,0.1

Type RM Length L Ch R = 1 ,3095.5  ,244.1,241.4,240.3
XS GIS Cut Line= 4
     1847706.633      599497.325      1847207.43      599412.379
     1847094.654      599399.669     1846660.587      599428.637
#Sta/Elev= 30
       0   835.2    29.2  829.02    48.7  822.15   116.9  787.05   175.3  763.46
     185  758.35   194.8  751.95   233.7  725.26   243.4  720.69   253.2  718.52
   262.9  717.49   438.2  701.72   515.8  696.44     582  694.03   591.5  693.95
   610.4  695.04   619.9  696.62   639.2  702.02   658.5   709.4   677.9  718.18
   706.9  733.68   764.9  768.76   832.6  804.84   851.9  813.89   880.9  824.96
   938.9  849.62   967.9  860.38   987.2  865.62  1006.6  868.53  1054.9  873.14
#Mann= 3 , 0 , 0
       0     .05       0     582    .045       0   610.4     .07       0
Bank Sta=582,610.4
XS Rating Curve= 0 ,0
Exp/Cntr=0.3,0.1

Type RM Length L Ch R = 1 ,2854.1  ,108.6,124.5,135.7
XS GIS Cut Line= 4
     1847793.005      599363.211     1847204.897      599163.558
     1847072.519      599170.069     1846684.064      599237.343
#Sta/Elev= 30
       0  768.67    29.1  766.18    58.2  762.36   135.9  747.89   174.7  741.41
   213.5   735.8   242.6  729.69   271.7  719.48   281.4  717.02   291.1  715.72
   388.2  706.74   436.7   703.3   533.7  698.43   668.4  693.46   687.3  692.94
   706.3  693.04   763.2  693.86   772.8   694.3   782.5  696.19   792.1  701.02
   801.7  707.43   811.3  712.68   907.5  749.21   917.1  753.83   936.3  764.82
   945.9  769.59  1061.3  809.98    1119  833.98  1138.2  839.42  1147.8  841.14
#Mann= 3 , 0 , 0
       0     .05       0   668.4    .045       0   706.3     .06       0
Bank Sta=668.4,706.3
XS Rating Curve= 0 ,0
Exp/Cntr=0.3,0.1

Type RM Length L Ch R = 1 ,2729.6  ,105.5,99.7,94.4
XS GIS Cut Line= 4
     1847923.647      599312.864     1847122.866       599098.02
     1846973.126      599063.298     1846608.543      599080.659
#Sta/Elev= 30
       0  729.47    58.5  726.23      78  727.76   107.3  726.92   136.6  723.06
   175.6  720.31   312.1   714.3   390.2  710.45   429.2  707.45   526.7  703.07
   653.5  698.37   877.1  692.62     906  692.47   925.2  693.09   944.4  695.05
   992.4  704.02    1002  707.18  1011.6  711.44    1050  730.63  1059.6  734.21
  1098.1  745.79  1146.1  763.15  1165.3   768.6  1184.5  772.63  1242.2     781
  1261.4   785.9  1290.2  795.17  1309.4  799.76  1328.6  800.32  1347.8  798.52
#Mann= 3 , 0 , 0
       0     .06       0   877.1    .045       0   925.2     .06       0
Bank Sta=877.1,925.2
XS Rating Curve= 0 ,0
Exp/Cntr=0.3,0.1

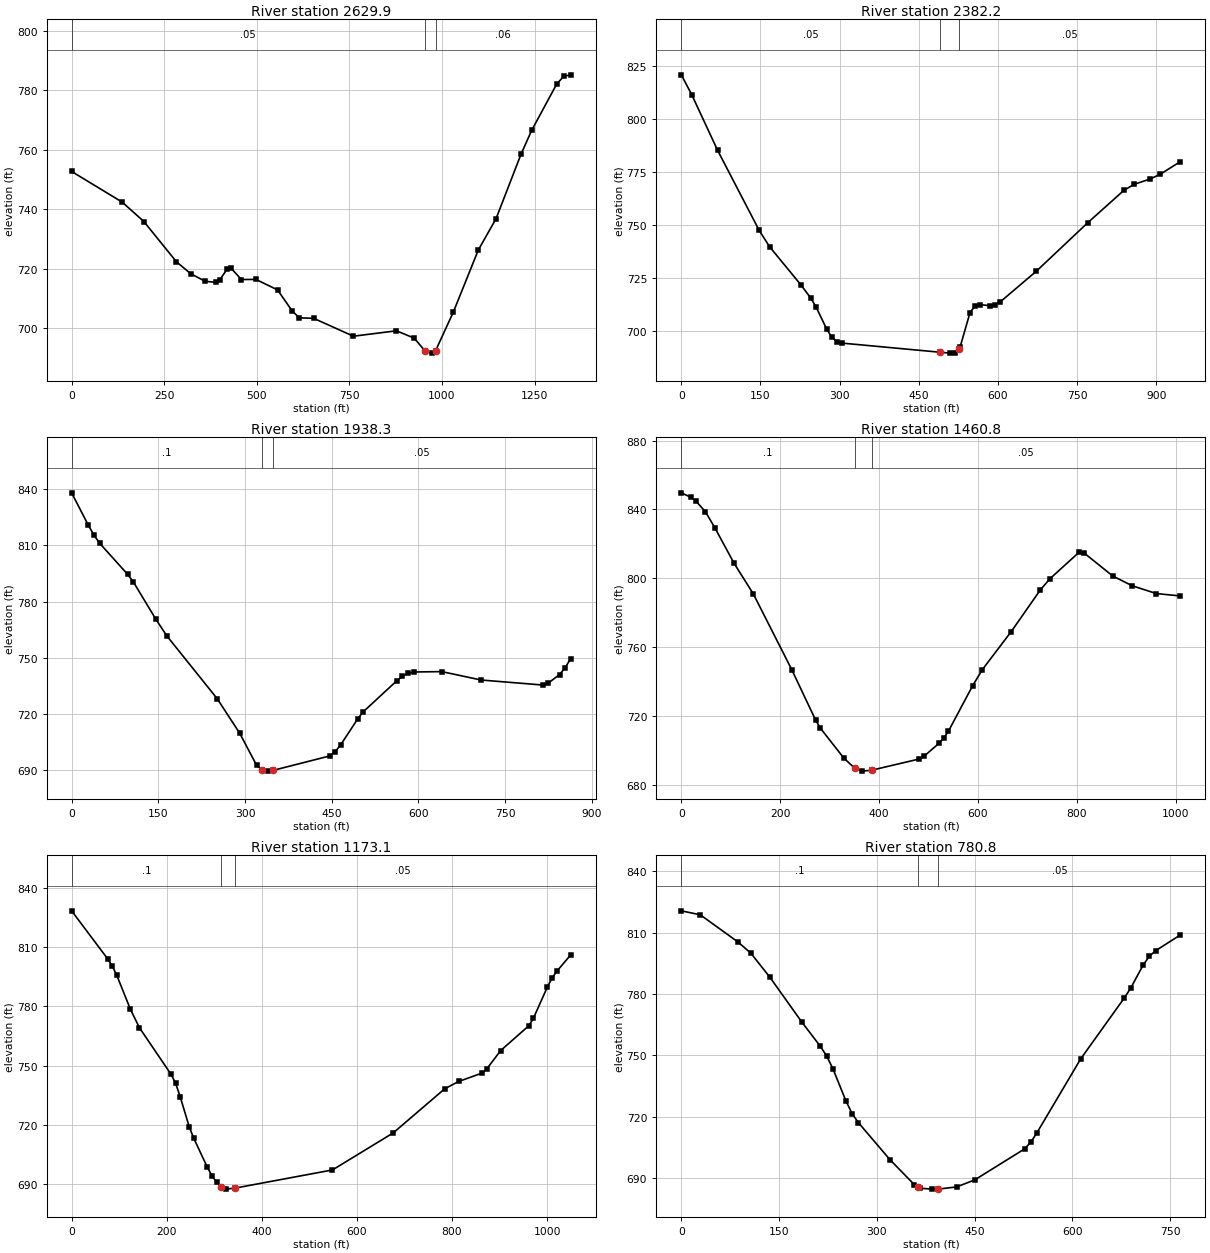
Type RM Length L Ch R = 1 ,2629.9  ,267.4,247.7,230.5
XS GIS Cut Line= 4
     1847930.157      599243.419     1847129.376      599028.575
     1846979.637      598993.853     1846615.053      599011.214
#Sta/Elev= 30
       0  752.74   136.6  742.43   195.1   735.9   282.9  722.39   321.9  718.32
   360.9   715.8   390.2  715.45   399.9  716.27   419.4  719.82   429.2   720.4
   458.4   716.4   497.5  716.44     556  712.92     595  705.93   614.5  703.52
   653.5  703.36   760.8  697.34   877.1  699.16   925.2  696.68     954  692.43
   973.2  691.65   982.8  692.47  1030.8  705.48  1098.1  726.32  1146.1  736.87
  1213.3  758.49  1242.2  766.56  1309.4  782.04  1328.6  784.74  1347.8  785.24
#Mann= 3 , 0 , 0
       0     .05       0     954    .045       0   982.8     .06       0
Bank Sta=954,982.8
XS Rating Curve= 0 ,0
Exp/Cntr=0.3,0.1

Type RM Length L Ch R = 1 ,2382.2  ,457.1,443.8,430.4
XS GIS Cut Line= 4
     1847402.814      598726.926     1846941.442      598755.572
     1846847.692      598798.975     1846523.039      598996.891
#Sta/Elev= 30
       0  820.62    19.7  811.28    68.8  784.98   147.5  747.26   167.2  739.54
   226.2  721.66   245.9  715.11   255.7   710.9   275.4  700.71   285.2   696.8
   295.1  694.77   304.9  694.06   490.4  689.76   509.2  689.34   518.6  689.56
   525.4  691.33     528     692   546.8  708.24   556.2  711.62   565.6  712.22
   585.1  711.73   594.8  712.15   604.6  713.58   672.8     728   770.3   750.9
   838.6  766.12     858  768.97   887.3  771.39   906.8  773.61   945.8  779.72
#Mann= 3 , 0 , 0
       0     .05       0   490.4    .045       0   525.4     .05       0
Bank Sta=490.4,525.4
XS Rating Curve= 0 ,0
Exp/Cntr=0.3,0.1

Type RM Length L Ch R = 1 ,1938.3  ,470.4,477.5,484
XS GIS Cut Line= 4
     1846778.682      598213.037     1846646.303      598449.582
      1846589.88      598540.728     1846320.782      598944.374
#Sta/Elev= 30
       0  838.11      29  820.73    38.7   815.5    48.4  811.19    96.8  794.57
   106.5  790.63   145.2   770.8   164.6  761.68   251.7  728.13   290.6   709.7
   319.8  692.61   329.8  689.88   339.3  689.37     349  689.82   446.2  697.46
   455.9  699.73   465.6  703.53   494.7  717.19   504.4  721.08   562.6   737.7
   572.3  740.05     582   741.6   591.7  742.35   640.2  742.56   708.2  738.07
   814.9  735.39   824.6  736.48     844  740.94   853.7  744.72   863.4  749.51
#Mann= 3 , 0 , 0
       0      .1       0   329.8    .045       0     349     .05       0
Bank Sta=329.8,349
XS Rating Curve= 0 ,0
Exp/Cntr=0.3,0.1

Type RM Length L Ch R = 1 ,1460.8  ,288.4,287.7,287.1
XS GIS Cut Line= 4
     1846507.414      597965.641      1846286.06      598169.634
     1846201.425      598243.419     1845995.262      598803.315
#Sta/Elev= 30
       0  849.62    19.4  847.01    29.1  844.97    48.6  838.71      68  829.26
   106.8  808.66   145.6  790.96   223.3     747   271.9  717.53   281.6  712.86
   329.1  695.45   350.9  689.69   366.5  687.98   385.2  688.53   481.8  695.05
   491.6  696.74   520.9  704.03   530.7  707.08   540.4  711.16   589.4  737.56
   608.9  746.89   667.6  769.06   726.3  793.19   745.9  799.75   804.5  815.02
   814.3  814.82     873  801.29   912.1  795.66     961  791.12  1009.9  789.71
#Mann= 3 , 0 , 0
       0      .1       0   350.9    .045       0   385.2     .05       0
Bank Sta=350.9,385.2
XS Rating Curve= 0 ,0
Exp/Cntr=0.3,0.1

Type RM Length L Ch R = 1 ,1173.1  ,381.1,392.3,403.3
XS GIS Cut Line= 4
     1846390.227      597831.093     1846132.848      597930.485
     1846047.779       598008.61     1845556.894      598447.412
#Sta/Elev= 30
       0   828.4    76.1  803.96    85.6  800.38    95.1  795.65   123.7  778.47
   142.7  769.12   209.3  745.48   218.8  740.97   228.3  734.21   247.4  718.89
   256.9  713.13   285.5   698.4   295.2  694.14   304.8  690.88   314.7  688.55
     324  687.37   343.3  687.87   548.6  697.09   676.4  715.86   784.5  738.18
     814  741.93   863.1  746.16   872.9  748.22   902.4  757.59   961.4  770.12
   971.2  773.92  1000.7  789.87  1010.5  794.35  1020.3  797.73  1049.8  806.11
#Mann= 3 , 0 , 0
       0      .1       0   314.7    .045       0   343.3     .05       0
Bank Sta=314.7,343.3
XS Rating Curve= 0 ,0
Exp/Cntr=0.3,0.1

Type RM Length L Ch R = 1 ,780.8   ,449.5,450.1,449.2
XS GIS Cut Line= 4
     1846342.484      597555.485     1846023.511      597584.081
     1845897.605      597616.249     1845604.203      597732.569
#Sta/Elev= 30
       0  820.58    29.1  818.64    87.3  805.29   106.8  799.86   135.9  788.16
   184.4  766.51   213.5  754.37   223.2  749.62   232.9  743.29   252.3  727.99
     262  721.63   271.7   717.2   320.2  699.09   357.4  686.96  362.42  685.94
   366.7  685.18   384.8  684.75   394.5  684.78   422.4  685.83   450.2  689.26
   526.7  704.39   536.3  707.74   545.8  712.36   612.8  748.36   679.7  778.08
   689.3  782.77   708.4  794.04     718  798.39   727.6  801.09   765.8  808.84
#Mann= 3 , 0 , 0
       0      .1       0  362.42    .045       0   394.5     .05       0
Bank Sta=362.42,394.5
XS Rating Curve= 0 ,0
Exp/Cntr=0.3,0.1

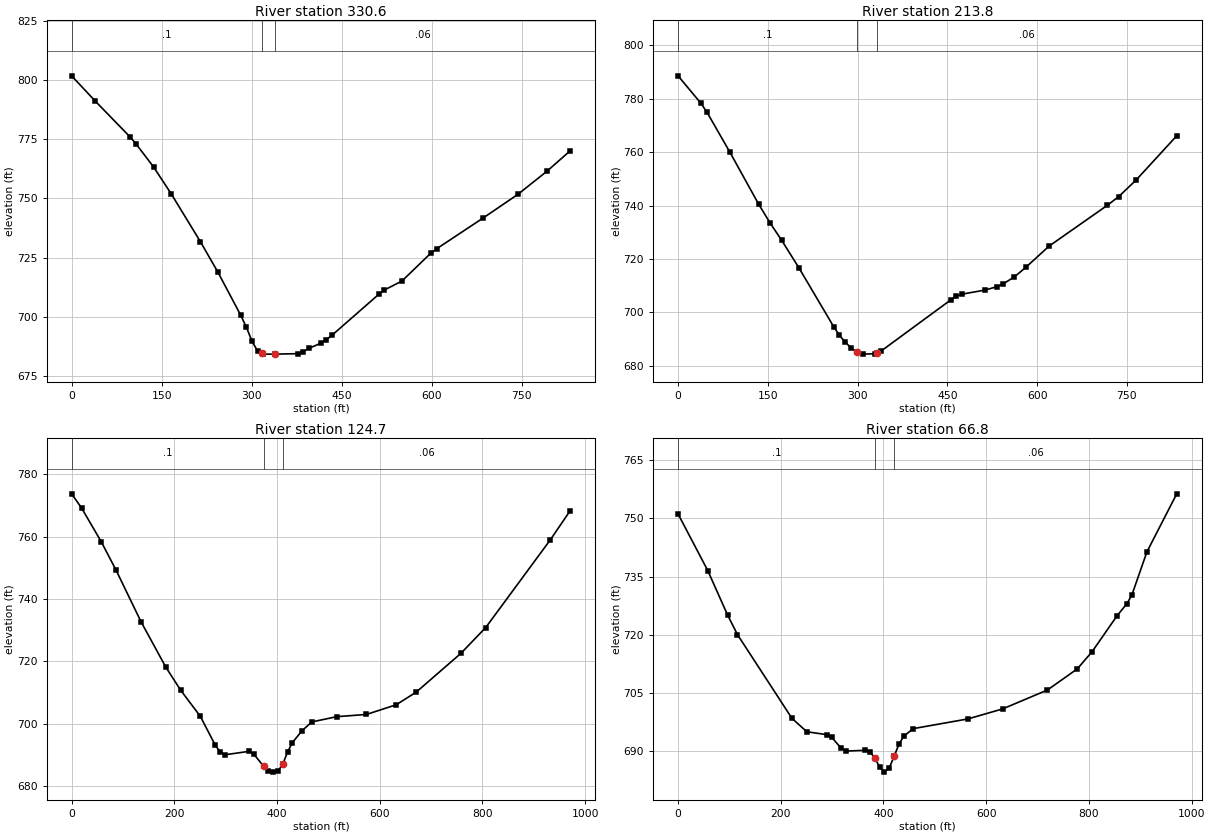
Type RM Length L Ch R = 1 ,330.6   ,128.8,116.8,104.2
XS GIS Cut Line= 4
     1846220.956      597199.582     1845977.901      597219.114
     1845832.501      597262.516     1845576.425      597614.513
#Sta/Elev= 30
       0   801.7      39  791.16    97.5  775.92   107.3  773.02   136.6  763.28
   165.8  752.04   214.6  731.81   243.8  718.94   281.8  700.78   291.3  695.69
   300.7  689.77   310.2  685.57   316.6  684.78   319.7   684.4   338.7   684.4
   376.6  684.59   386.1  685.46   395.6  686.86   414.9  688.94   424.6  690.48
   434.3  692.45   511.7  709.58   521.3  711.45   550.4   715.2   598.7  726.99
   608.4  728.83   685.8  741.79   743.8  751.78   792.2  761.52   830.9  770.13
#Mann= 3 , 0 , 0
       0      .1       0   316.6    .045       0   338.7     .06       0
Bank Sta=316.6,338.7
XS Rating Curve= 0 ,0
Exp/Cntr=0.3,0.1

Type RM Length L Ch R = 1 ,213.8   ,97.4,89.2,81.1
XS GIS Cut Line= 4
      1846092.05      597032.916     1845857.675      597119.721
     1845762.189       597218.68      1845538.23      597604.096
#Sta/Elev= 30
       0  788.57    38.4  778.23    48.1  775.02    86.5  760.03   134.6  740.54
   153.8  733.48     173  727.04   201.9  716.71   259.8  694.74   269.6  691.44
   279.4  688.89   289.2  686.68     299  685.01   308.9   684.4   328.5  684.55
   332.6  684.86   338.3   685.4   455.3  704.64     465  706.06   474.7  706.86
   513.4   708.4   532.8  709.66   542.5   710.6   561.9   713.3   581.3  716.93
     620  724.85   716.9  740.04   736.3  743.38   765.4  749.58   833.2  766.12
#Mann= 3 , 0 , 0
       0      .1       0     299    .045       0   332.6     .06       0
Bank Sta=299,332.6
XS Rating Curve= 0 ,0
Exp/Cntr=0.3,0.1

Type RM Length L Ch R = 1 ,124.7   ,57.8,57.8,57.8
XS GIS Cut Line= 4
     1846059.064      596947.846     1845767.397      597048.541
     1845708.369      597185.694     1845454.897      597631.874
#Sta/Elev= 30
       0  773.77    19.3  769.26    57.8  758.37    86.8  749.19     135  732.76
   183.2  718.19   212.1  710.78   250.7  702.31   279.6  693.11   289.3  690.86
   298.9  689.99   345.9  691.09   355.2  690.11   373.9  686.28   383.2  684.76
   392.6  684.41   401.9  684.79   411.2  686.95   420.6  690.93   429.9  693.89
   448.5  697.66   467.6  700.52     516  702.21   574.1  702.93   632.2  706.05
   670.9  710.08     758  722.54   806.4  730.84   932.3  759.03     971   768.4
#Mann= 3 , 0 , 0
       0      .1       0   373.9    .045       0   411.2     .06       0
Bank Sta=373.9,411.2
XS Rating Curve= 0 ,0
Exp/Cntr=0.3,0.1

Type RM Length L Ch R = 1 ,66.8    ,67.9,66.8,65.7
XS GIS Cut Line= 4
     1846010.453       596914.86     1845718.786      597015.555
     1845659.758      597152.707     1845406.286      597598.888
#Sta/Elev= 30
       0  751.14    57.8  736.56    96.4   725.1   115.7  720.04   221.8  698.46
   250.7  695.02   289.3  694.27   298.9  693.62   317.9  690.74   327.2  690.04
   364.6  690.23   373.9  689.76   383.2  688.28   392.6  685.86   401.9  684.61
   411.2  685.66   420.6  688.66   429.9  691.73   439.2  693.83   457.9  695.82
   564.4  698.32   632.2  700.91   719.3  705.78   777.4  711.22   806.4  715.68
   854.8  724.91   874.2  728.06   883.9  730.34   912.9  741.36     971  756.33
#Mann= 3 , 0 , 0
       0      .1       0   383.2    .045       0   420.6     .06       0
Bank Sta=383.2,420.6
XS Rating Curve= 0 ,0
Exp/Cntr=0.3,0.1

Chan Stop Cuts=-1
Use User Specified Reach Order=0
Composite Channel Slope=5